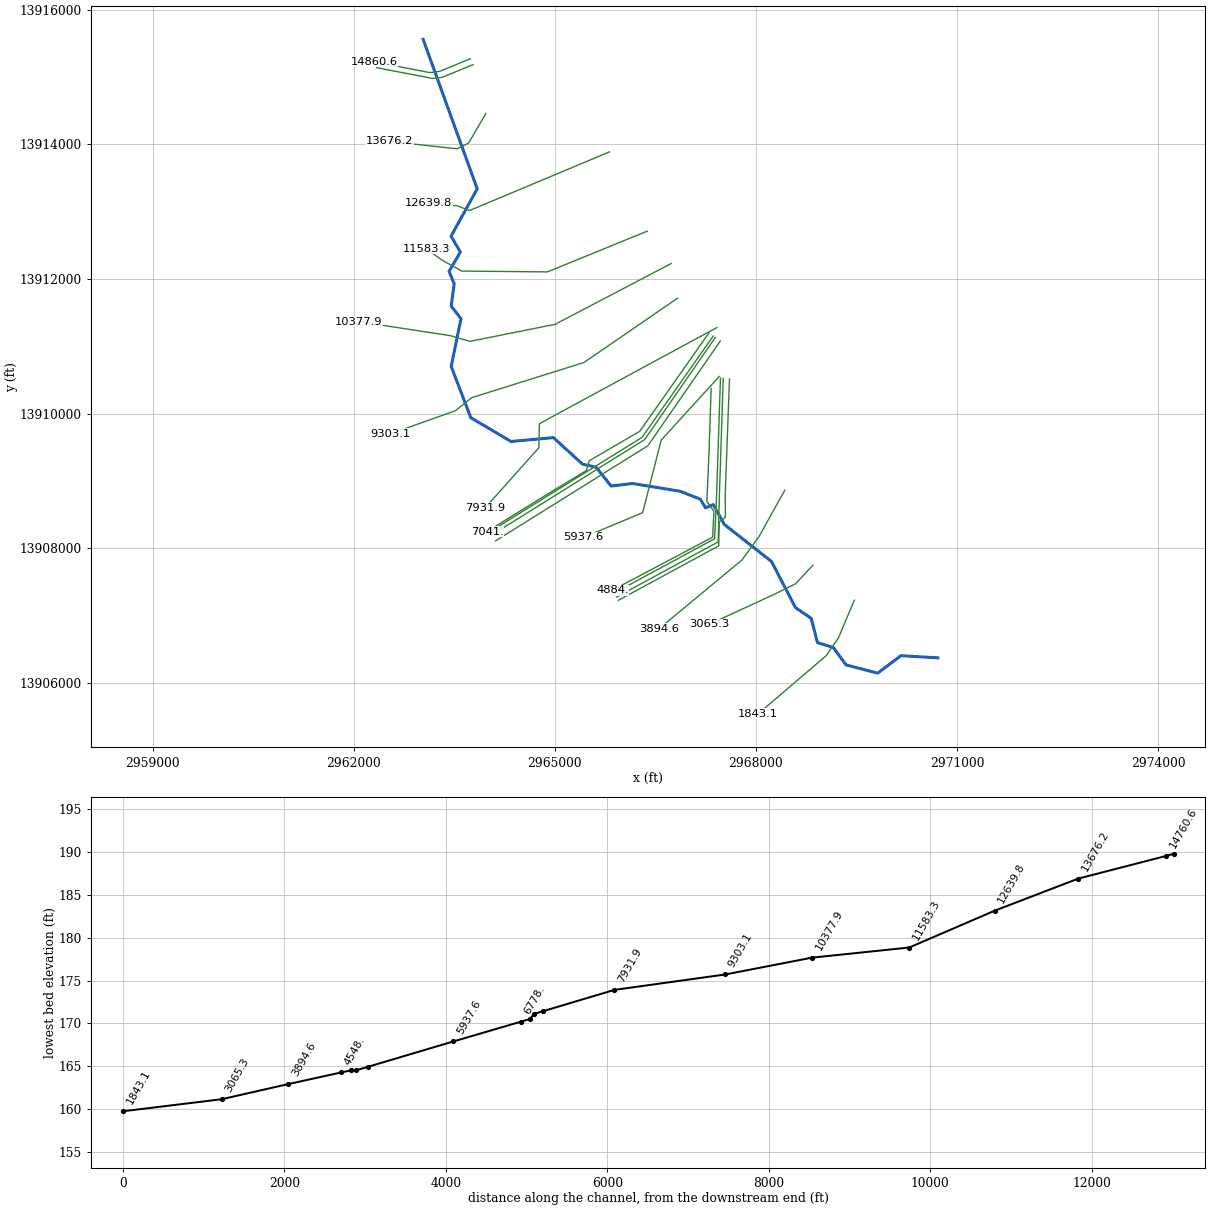
--- K160-01-00.prj (project) ---

Proj Title=K160-01-00
Current Plan=p06
Default Exp/Contr=0.3,0.1
English Units
Geom File=g02
Flow File=f06
Flow File=f05
Plan File=p06
Plan File=p05
Y Axis Title=Elevation
X Axis Title(PF)=Main Channel Distance
X Axis Title(XS)=Station
BEGIN DESCRIPTION:
Cypress Creek Watershed
Rock Hollow Trib 1.63
HCFCD Unit K160-01-00
Flood Hazard Model
10, 2, 1, 0.2%
Filename K160-01-00
Prepared by:  Halff Associates Inc  DATE:  March 26, 2004
Reviewed by:  _____________________  DATE:  __________________
STATUS (Final)
TROPICAL STORM ALLISON RECOVERY PROJECT
END DESCRIPTION:
DSS File=dss
DSS Export Rating Curves= 0
DSS Export Rating Curve Sorted= 0
DSS Export Volume Flow Curves= 0
DXF OffsetX= 0
DXF OffsetY= 0
DXF ScaleX= 1
DXF ScaleY= 10

--- K160-01-00.p06 (plan) ---

Plan Title=Effective FW 2013
Program Version=3.13
Short Identifier=Eff FW 2013
Geom File=g02
Flow File=f06
Subcritical Flow
K Sum by GR= 0
Std Step Tol= 0.01
Critical Tol= 0.01
Num of Std Step Trials= 20
Max Error Tol= 0.3
Flow Tol Ratio= 0.001
Split Flow NTrial= 30
Split Flow Tol= 0.02
Split Flow Ratio= 0.02
Log Output Level= 0
Friction Slope Method= 1
Unsteady Friction Slope Method= 2
Unsteady Bridges Friction Slope Method= 1
Parabolic Critical Depth
Global Vel Dist= 0 , 0 , 0
Global Log Level= 0
CheckData=True
Encroach Param=-1 ,0,0, 2
Encroach River=K160-01-00
Encroach Reach=K160-01-00_0018
Encroach Node=14860.6
       1  4988.4 5107.58
Encroach Node=14760.6
       1    4975    5115
Encroach Node=13676.2
       1 4958.66 5088.25
Encroach Node=12639.8
       1  4969.3  5046.2
Encroach Node=11583.3
       1 4775.73    5011
Encroach Node=10377.9
       1    4840    5015
Encroach Node=9303.1
       1    4985    5289
Encroach Node=7931.9
       1    4805    5020
Encroach Node=7041.
       1    4905    5059
Encroach Node=6939.4
       1    4930    5100
Encroach Node=6880.6
       1    4885    5100
Encroach Node=6778.
       1 4812.17  5031.7
Encroach Node=5937.6
       1    4940    5045
Encroach Node=4884.
       1    4955    5375
Encroach Node=4732.9
       1    4915    5305
Encroach Node=4673.1
       1    4900    5300
Encroach Node=4548.
       1    4915    5225
Encroach Node=3894.6
       1    4830    5045
Encroach Node=3065.3
       1    4880    5110
Encroach Node=1843.1
       1    4820    5180
BEGIN DESCRIPTION:
FEMA Effective Floodway October 2013
TSARP geometry modified at RS 1843.1 to match 2001 LiDAR dataset.  Low area in right overbank does not appear in the LiDAR.
END DESCRIPTION:
Computation Interval=1HOUR
Output Interval=1HOUR
Run HTab= 0
Run UNet= 0
Run PostProcess= 0
UNET Theta= 1
UNET Theta Warmup= 1
UNET ZTol= 0.02
UNET ZSATol= 0.1
UNET MxIter= 20
UNET MaxInSteps= 20
UNET DtIC= 0
UNET DtMin= 0
UNET MaxCRTS= 20
UNET WFStab= 2
UNET SFStab= 1
UNET WFX= 1
UNET SFX= 1
UNET DSS MLevel= 4
UNET DZMax Abort= 100
UNET Convert EG Bridges=-1
UNET Use Existing IB Tables=-1
UNET Froude Reduction=False
UNET Froude Limit= 1
UNET Froude Power= 10
Instantaneous Interval=1HOUR
DSS File=dss
Write IC File= 0
IC Time=0,,
Echo Input=False
Echo Output=False
Write Detailed= 0
Detailed Automatic Start=False, 10

--- K160-01-00.p05 (plan) ---

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Plan Title=Effective MP 2013
Short Identifier=Eff MP 2013
Geom File=g02
Flow File=f05
Encroach Param=-1 ,0,0, 0
FEMA Effective MP October 2013

--- K160-01-00.f06 (steady flow) ---

Flow Title=Effective FW 2013
Program Version=3.13
Number of Profiles= 2
Profile Names=1PCT_100yr,1PCTFloodway_10
River Rch & RM=K160-01-00,K160-01-00_0018       ,14860.6
     499     499
River Rch & RM=K160-01-00,K160-01-00_0018       ,13676.2
     528     528
River Rch & RM=K160-01-00,K160-01-00_0018       ,12639.8
     556     556
River Rch & RM=K160-01-00,K160-01-00_0018       ,10377.9
     583     583
River Rch & RM=K160-01-00,K160-01-00_0018       ,9303.1
     589     589
River Rch & RM=K160-01-00,K160-01-00_0018       ,7931.9
     641     641
River Rch & RM=K160-01-00,K160-01-00_0018       ,6939.4
     646     646
River Rch & RM=K160-01-00,K160-01-00_0018       ,4732.9
     710     710
River Rch & RM=K160-01-00,K160-01-00_0018       ,3894.6
     743     743
River Rch & RM=K160-01-00,K160-01-00_0018       ,3065.3
     817     817
River Rch & RM=K160-01-00,K160-01-00_0018       ,1843.1
     904     904
Boundary for River Rch & Prof#=K160-01-00,K160-01-00_0018       , 1
Up Type= 0
Dn Type= 3
Dn Slope=0.00069
Boundary for River Rch & Prof#=K160-01-00,K160-01-00_0018       , 2
Up Type= 0
Dn Type= 3
Dn Slope=0.00069
DSS Import GetInterval= 0
DSS Import GetPeak= 0
DSS Import FillOption= 0

--- K160-01-00.f05 (steady flow) ---

Flow Title=Effective MP 2013
Program Version=3.13
Number of Profiles= 4
Profile Names=10PCT_10yr,2PCT_50yr,1PCT_100yr,0.2PCT_500yr
River Rch & RM=K160-01-00,K160-01-00_0018       ,14860.6
     188     379     499     896
River Rch & RM=K160-01-00,K160-01-00_0018       ,13676.2
     199     401     528     947
River Rch & RM=K160-01-00,K160-01-00_0018       ,12639.8
     210     422     556     998
River Rch & RM=K160-01-00,K160-01-00_0018       ,10377.9
     220     443     583    1047
River Rch & RM=K160-01-00,K160-01-00_0018       ,9303.1
     222     447     589    1057
River Rch & RM=K160-01-00,K160-01-00_0018       ,7931.9
     242     487     641    1150
River Rch & RM=K160-01-00,K160-01-00_0018       ,6939.4
     244     491     646    1160
River Rch & RM=K160-01-00,K160-01-00_0018       ,4732.9
     268     539     710    1275
River Rch & RM=K160-01-00,K160-01-00_0018       ,3894.6
     280     564     743    1333
River Rch & RM=K160-01-00,K160-01-00_0018       ,3065.3
     308     620     817    1466
River Rch & RM=K160-01-00,K160-01-00_0018       ,1843.1
     341     686     904    1622
Boundary for River Rch & Prof#=K160-01-00,K160-01-00_0018       , 1
Up Type= 0
Dn Type= 3
Dn Slope=0.00069
Boundary for River Rch & Prof#=K160-01-00,K160-01-00_0018       , 2
Up Type= 0
Dn Type= 3
Dn Slope=0.00069
Boundary for River Rch & Prof#=K160-01-00,K160-01-00_0018       , 3
Up Type= 0
Dn Type= 3
Dn Slope=0.00069
Boundary for River Rch & Prof#=K160-01-00,K160-01-00_0018       , 4
Up Type= 0
Dn Type= 3
Dn Slope=0.00069
DSS Import GetInterval= 0
DSS Import GetPeak= 0
DSS Import FillOption= 0

--- K160-01-00.g02 (geometry) ---

Geom Title=K160-01-00 2013
Program Version=3.13

River Reach=K160-01-00      ,K160-01-00_0018
Reach XY= 30
      2963035.23     13915559.22      2963842.85     13913339.02
      2963452.41     13912635.87       2963591.4     13912399.61
      2963422.29     13912114.51      2963499.32     13911928.57
      2963454.16     13911597.43      2963600.98      13911411.1
      2963454.16     13910702.29      2963747.67     13909939.66
      2964347.55     13909587.76      2964978.82     13909644.97
      2965413.94     13909250.98      2965617.12     13909205.38
      2965839.93     13908926.38      2966161.08     13908963.51
      2966871.64     13908848.09      2967171.73     13908730.67
      2967249.01     13908602.21      2967364.06     13908650.61
      2967529.87     13908355.33      2968233.55     13907805.34
      2968590.84     13907120.87      2968825.64     13906961.04
       2968917.8     13906601.65      2969156.23     13906527.59
      2969344.71     13906270.48      2969816.75     13906148.18
      2970164.54     13906407.12      2970715.25       13906375.

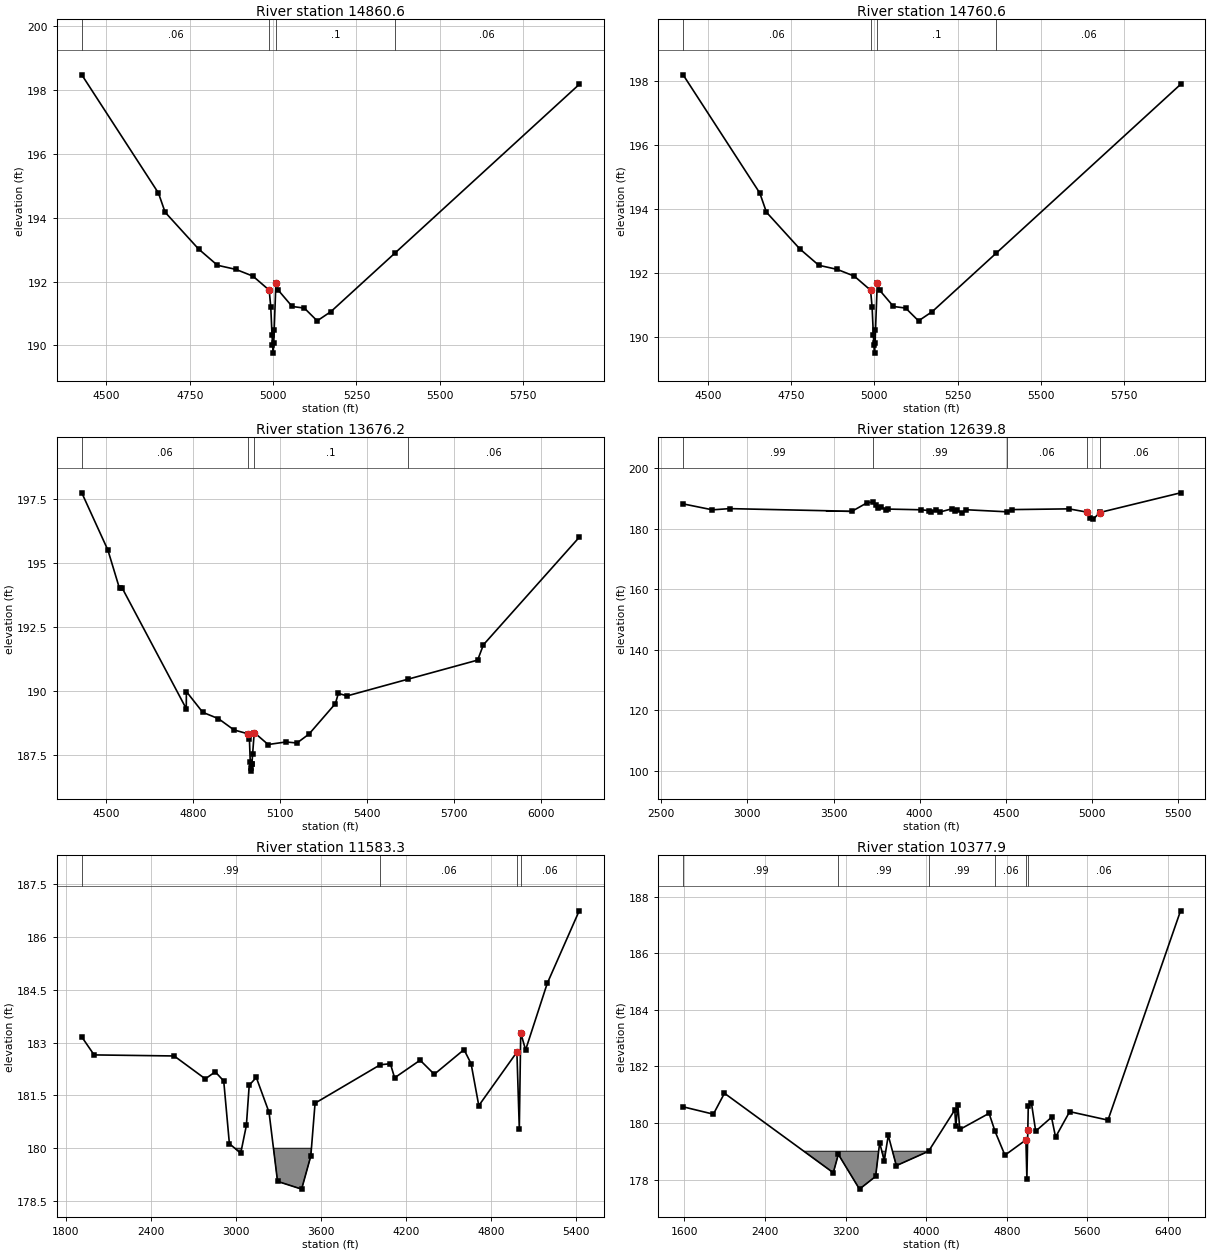
Type RM Length L Ch R = 1 ,14860.6 ,100,100,100
BEGIN DESCRIPTION:
Cross Section K160-01-00-X10
END DESCRIPTION:
XS GIS Cut Line= 4
      2963740.07       13915270.      2963281.02      13915082.4
      2963135.54      13915064.6      2962300.79      13915224.8
#Sta/Elev= 22
    4426  198.47    4656  194.77    4676  194.17  4776.3  193.02    4833  192.51
  4888.5  192.38  4939.5  192.17  4988.4  191.73    4993   191.2  4996.8  190.34
  4998.2  190.03  5000.3  189.76    5002  190.07  5003.2  190.48  5008.5  191.95
  5015.5  191.73  5057.2  191.22  5093.7  191.17  5132.3  190.77  5173.6  191.06
  5365.5  192.89  5918.5  198.17
#Mann= 4 ,-1 , 0
    4426     .06       0  4988.4    .055       0  5008.5      .1       0
  5365.5     .06       0
Bank Sta=4988.4,5008.5
Exp/Cntr=0.3,0.1

Type RM Length L Ch R = 1 ,14760.6 ,1075,1084.4,1125.3
BEGIN DESCRIPTION:
Cross Section K160-01-00-X10
END DESCRIPTION:
XS GIS Cut Line= 4
 2963781.756235913915183.0023939       2963322.7     13914995.43
      2963177.22     13914977.61 2962342.478594613915137.8357799
#Sta/Elev= 22
    4426   198.2    4656   194.5    4676   193.9  4776.3  192.75    4833  192.24
  4888.5  192.11  4939.5   191.9  4988.4  191.46    4993  190.93  4996.8  190.07
  4998.2  189.76  5000.3  189.49    5002   189.8  5003.2  190.21  5008.5  191.68
  5015.5  191.46  5057.2  190.95  5093.7   190.9  5132.3   190.5  5173.6  190.79
  5365.5  192.62  5918.5   197.9
#Mann= 4 ,-1 , 0
    4426     .06       0  4988.4    .055       0  5008.5      .1       0
  5365.5     .06       0
Bank Sta=4988.4,5008.5
Exp/Cntr=0.3,0.1

Type RM Length L Ch R = 1 ,13676.2 ,1019.6,1036.4,946.8
BEGIN DESCRIPTION:
Cross Section K160-01-00-X9
END DESCRIPTION:
XS GIS Cut Line= 4
 2963971.9492389 13914459.363955      2963714.64     13914018.02
      2963541.12     13913933.48 2962536.888921613914041.7461549
#Sta/Elev= 29
  4416.8  197.74  4506.8   195.5  4546.8     194  4556.8     194  4776.8   189.3
  4777.2  189.97  4833.5  189.16  4887.8  188.91  4941.2  188.47  4989.3  188.32
  4994.4  188.12  4997.3  187.21  4998.3  186.97  4999.9  186.86  5001.6  187.12
  5002.7  187.12  5005.4  187.52  5010.9  188.37  5058.9   187.9  5120.2     188
  5158.3  187.96  5199.8  188.31  5290.7   189.5  5300.7   189.9  5330.7   189.8
  5539.4  190.45  5780.7   191.2  5800.7   191.8  6130.7     196
#Mann= 4 ,-1 , 0
  4416.8     .06       0  4989.3    .055       0  5010.9      .1       0
  5539.4     .06       0
Bank Sta=4989.3,5010.9
Exp/Cntr=0.3,0.1

Type RM Length L Ch R = 1 ,12639.8 ,1070.3,1056.5,971.4
BEGIN DESCRIPTION:
Cross Section K160-01-00-X8
END DESCRIPTION:
XS GIS Cut Line= 4
     2965816.935    13913888.115      2963728.65     13913016.83
        2963544.     13913087.13 2963118.196079613913123.7466101
#Sta/Elev= 30
    2627  188.15    2797  186.19    2897  186.59    3607  185.71    3697  188.59
    3727   188.7    3747  187.92    3757  186.85    3777   187.2    3807  186.07
    3817  186.44    4007  186.21    4057  185.93    4067  185.42    4097  186.16
    4117  185.46    4187  186.52    4207  185.83    4217  186.19    4247  185.11
    4267  186.23    4507  185.54    4537  186.27    4867  186.51  4969.3  185.46
  4990.7  183.42  5007.5  183.12  5046.2   185.3  5048.7  185.35  5514.7   191.8
#Mann= 6 ,-1 , 0
    2627     .99       0    3727     .99       0    4507     .06       0
  4969.3     .07       0  5046.2     .08       0  5048.7     .06       0
#Block Obstruct= 2 ,-1
    2000  4039.3   185.9    5000    5010     100
Bank Sta=4969.3,5046.2
Exp/Cntr=0.3,0.1

Type RM Length L Ch R = 1 ,11583.3 ,1066.5,1205.4,1087.3
BEGIN DESCRIPTION:
Cross Section K160-01-00-X7;  Blocked obstruction on left because flow in this area have to exceed elevation 180 for conveyance downstream
raw = levee at 4036 at 182 = removed for now
END DESCRIPTION:
XS GIS Cut Line= 6
 2966379.444343213912710.2043173      2966349.61     13912698.09
      2964890.44     13912105.59      2963614.21     13912117.66
       2963316.7     13912279.94  2963081.65872613912449.7805425
#Sta/Elev= 30
  1911.7  183.16  1998.7  182.65  2563.9  182.62  2783.9  181.97  2853.9  182.17
  2913.9  181.91  2953.9  180.13  3033.9  179.86  3073.9  180.65  3093.9  181.79
  3143.9  182.01  3233.9  181.02  3293.9  179.06  3463.9  178.84  3528.8  179.78
  3558.8  181.28  4018.8  182.37  4090.6   182.4  4120.6     182  4300.6   182.5
  4400.6   182.1  4610.6   182.8  4660.6   182.4  4714.9  181.21    4984  182.73
    5001  180.55    5011  183.28  5045.3  182.79  5198.2  184.68  5423.9  186.74
#Mann= 4 ,-1 , 0
  1911.7     .99       0  4018.8     .06       0    4984     .07       0
    5011     .06       0
#Block Obstruct= 1 ,-1
    1500    4000     180
Bank Sta=4984,5011
Exp/Cntr=0.3,0.1

Type RM Length L Ch R = 1 ,10377.9 ,888.4,1074.8,1199.6
BEGIN DESCRIPTION:
Cross Section K160-01-00-X6; Blocked obstruction on left because conveyance downstream blocked by contour 179. RAW
raw = levee at 4314 at 180.1 = removed for now
END DESCRIPTION:
XS GIS Cut Line= 5
      2966737.79     13912230.58      2965003.75     13911326.72
      2963733.57     13911074.06      2963440.75     13911159.14
  2962076.40005913911366.5911087
#Sta/Elev= 30
  1588.8  180.57  1888.8  180.31  1998.8  181.05  3078.8  178.24  3128.8  178.89
  3338.8  177.66  3498.8  178.11  3538.8   179.3  3584.3  178.67  3624.3  179.56
  3704.3  178.49  4024.3     179  4284.3  180.46  4294.3  179.88  4314.3  180.63
  4334.3  179.77  4624.3  180.34  4684.1   179.7  4781.8  178.86    4990   179.4
  4999.7  178.02  5008.7  179.74  5013.5  180.59  5044.1  180.72    5087  179.71
  5244.2   180.2  5284.2   179.5  5424.2   180.4  5804.2   180.1  6524.3   187.5
#Mann= 6 ,-1 , 0
  1588.8     .99       0  3128.8     .99       0  4024.3     .99       0
  4684.1     .06       0    4990    .055       0  5008.7     .06       0
#XS Ineff= 2 , 0
       0    4990   179.4  5008.7       0  179.74
Permanent Ineff=
       F       F
#Block Obstruct= 1 ,-1
    1000    4100     179
Bank Sta=4990,5008.7
Exp/Cntr=0.3,0.1

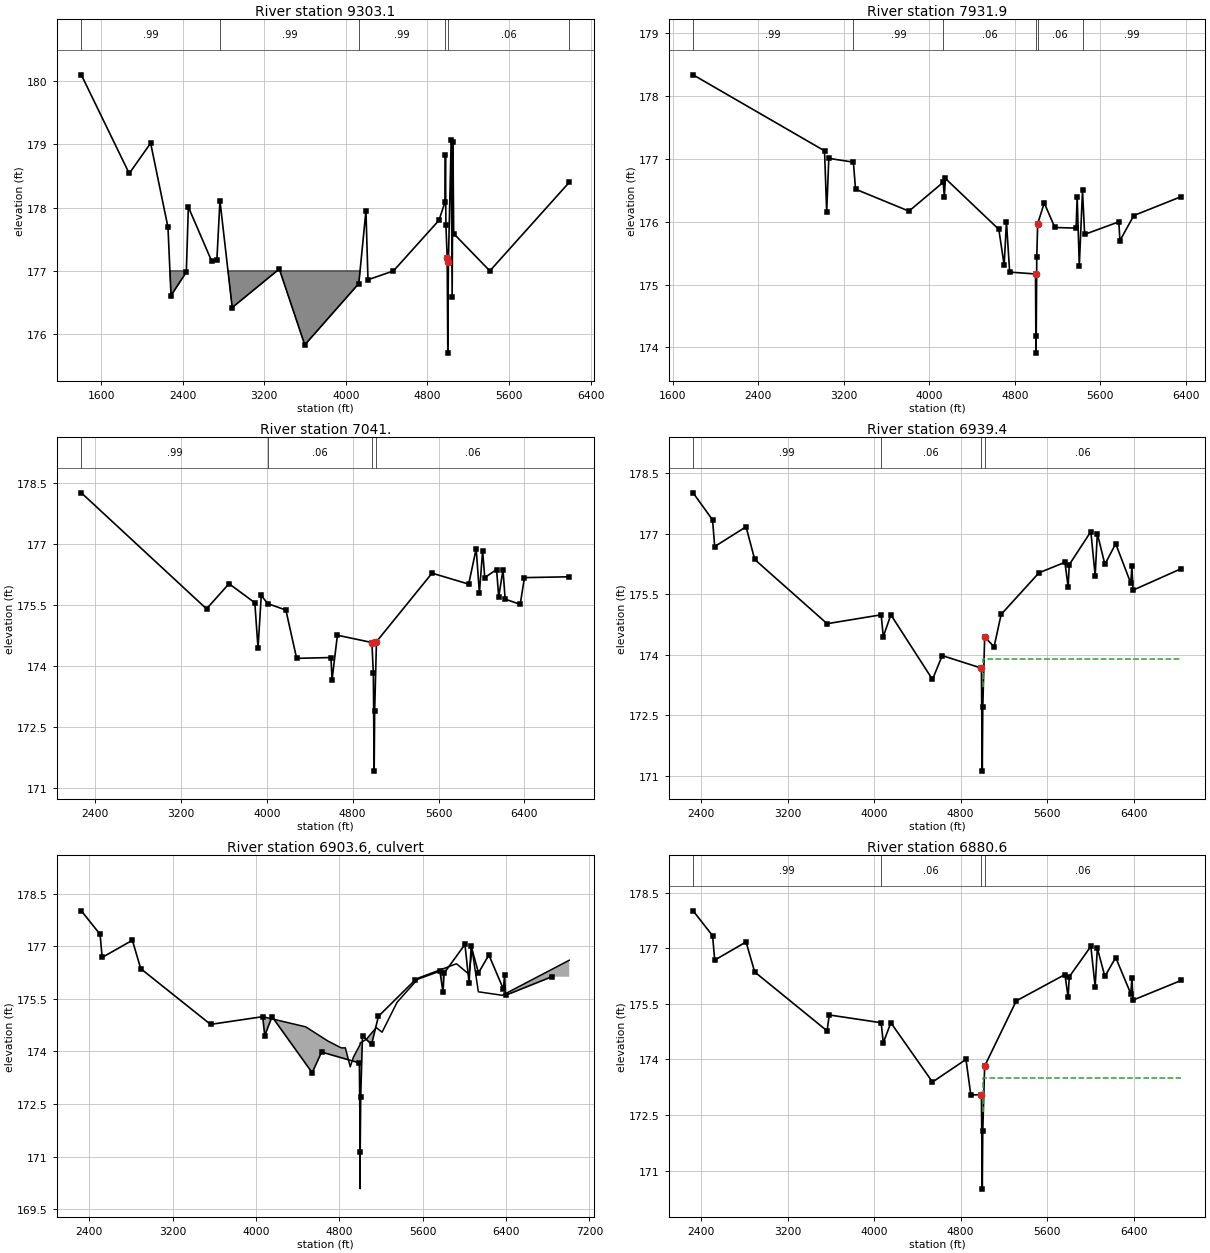
Type RM Length L Ch R = 1 ,9303.1  ,966.7,1371.2,1412.8
BEGIN DESCRIPTION:
Cross Section K160-01-00-X5; Blocked obstruction on left because conveyance in this area has to exceed elev. 178.
raw = levee at 4197.1 at 178 = removed for now
END DESCRIPTION:
XS GIS Cut Line= 5
      2966831.29      13911714.9      2965434.43     13910760.04
      2963761.22     13910238.19      2963516.23     13910044.08
       2962546.2     13909701.05
#Sta/Elev= 30
  1405.1   180.1  1875.1  178.54  2085.1  179.02  2255.1  177.69  2285.1  176.61
  2435.1  176.98  2455.1  178.01  2685.1  177.15  2735.1  177.18  2765.1  178.11
  2885.1  176.42  3347.1  177.03  3597.1  175.83  4127.1   176.8  4197.1  177.95
  4217.1  176.86  4467.1     177  4913.5   177.8  4972.8  178.09  4976.9  178.84
  4981.4  177.73    4994  177.21  5000.1   175.7  5005.8  177.14  5033.2  179.07
  5042.7  176.59  5050.6  179.04  5057.7  177.59  5412.4     177  6191.2   178.4
#Mann= 6 ,-1 , 0
  1405.1     .99       0  2765.1     .99       0  4127.1     .99       0
  4976.9     .04       0  5005.8     .06       0  6191.2     .04       0
#Block Obstruct= 1 ,-1
    1000    4191     177
Bank Sta=4994,5005.8
Exp/Cntr=0.3,0.1

Type RM Length L Ch R = 1 ,7931.9  ,890.9,890.9,739
BEGIN DESCRIPTION:
Cross Section K160-01-00-X4
Mod left ob RAW Aug 2003
Check flows to Stream 172-00-00 on right overbank
END DESCRIPTION:
XS GIS Cut Line= 5
      2967417.81     13911278.55      2965391.92      13910187.7
      2964770.57     13909851.32      2964762.42     13909494.77
       2963959.5     13908600.43
#Sta/Elev= 30
    1790  178.34    3020  177.13    3040  176.16    3060  177.01    3290  176.95
    3310  176.52    3810  176.17  4130.9  176.63  4140.9   176.4  4150.9  176.69
  4650.9  175.88  4700.9  175.31  4722.4     176  4752.4   175.2  4994.4  175.17
  4997.6  174.18  4999.9  173.91  5006.1  175.44  5014.6  175.97  5076.1   176.3
  5175.3  175.91  5374.1   175.9  5384.1   176.4  5404.1   175.3  5434.1   176.5
  5454.1   175.8  5774.1     176  5784.1   175.7  5914.1   176.1    6356   176.4
#Mann= 6 ,-1 , 0
    1790     .99       0    3290     .99       0  4130.9     .06       0
  4994.4     .04       0  5014.6     .06       0  5434.1     .99       0
Bank Sta=4994.4,5014.6
Exp/Cntr=0.3,0.1

Type RM Length L Ch R = 1 ,7041.   ,122,101.6,38
BEGIN DESCRIPTION:
PRIVATE DRIVE - XS 4
Interpolated channel - LIDAR overbanks
END DESCRIPTION:
XS GIS Cut Line= 6
      2967297.82     13911197.86       2966267.5     13909738.62
      2965514.04     13909301.16      2965472.18     13909156.41
      2964897.36     13908809.87      2963988.56      13908250.6
#Sta/Elev= 30
  2271.3  178.27    3438  175.41    3648  176.03    3888  175.56    3918  174.44
    3948  175.74    4008  175.54  4177.6  175.38  4277.6  174.19  4597.6  174.21
  4607.6  173.66  4657.6  174.76  4978.9  174.58 4992.51  173.82 5000.08  171.41
 5004.71  172.89 5021.51   174.6  5539.5  176.29  5880.7  176.02  5950.7  176.89
  5980.7   175.8  6010.7  176.84  6030.7  176.18  6140.7  176.38  6160.7  175.71
  6200.7  176.37  6220.7  175.65  6360.7  175.52  6400.7  176.18  6817.8   176.2
#Mann= 4 ,-1 , 0
  2271.3     .99       0    4008     .06       0  4978.9     .04       0
 5021.51     .06       0
Bank Sta=4978.9,5021.51
Exp/Cntr=0.5,0.3

Type RM Length L Ch R = 1 ,6939.4  ,58.8,58.8,58.8
BEGIN DESCRIPTION:
PRIVATE DRIVE - XS 3
Interpolated channel - LIDAR overbanks
Upstream Section of Bridge/Culvert/Weir
END DESCRIPTION:
XS GIS Cut Line= 4
     2967364.709    13911154.217     2966300.473    13909646.939
     2965452.848    13909125.178     2964028.012    13908245.586
#Sta/Elev= 30
  2324.4  178.01  2504.4  177.34  2524.4  176.68  2814.4  177.17  2894.4  176.36
  3564.4  174.77  4064.4  174.99  4084.4  174.45  4154.4  174.99  4539.5  173.39
  4629.5  173.98  4992.3  173.67  5000.1  171.12  5004.9   172.7  5022.3  174.44
  5109.5   174.2  5174.9     175  5524.9  176.03  5764.9  176.29  5794.9  175.68
  5804.9  176.23  6004.9  177.05  6044.9  175.96  6064.9     177  6134.9  176.24
  6234.9  176.75  6374.9  175.77  6384.9  176.19  6394.9   175.6  6839.3  176.13
#Mann= 4 ,-1 , 0
  2324.4     .99       0  4064.4     .06       0  4992.3     .04       0
  5022.3     .06       0
#XS Ineff= 2 , 0
       0    4986   173.6    5010       0   173.9
Permanent Ineff=
       F       F
Bank Sta=4992.3,5022.3
Exp/Cntr=0.5,0.3

Type RM Length L Ch R = 2 ,6903.6  ,,,
BEGIN DESCRIPTION:
PRIVATE DRIVE
Structure ID: K160-01-00-S2
END DESCRIPTION:
Bridge Culvert--1,0,-1,-1, 0
Deck Dist Width WeirC Skew NumUp NumDn MinLoCord MaxHiCord MaxSubmerge Is_Ogee
10,26,3,0, 21, 21, , , 0.95, 0, ,,,
  4064.4  4477.7  4687.7  4817.7  4857.7  4904.7  4934.3  4998.2    5000    5059
    5107    5155    5210  5353.8  5563.8  5923.8  6043.8  6073.8  6133.8  6363.8
  7005.7
  174.99   174.7   174.3   174.1   174.1  173.56  173.83  174.19 174.243 174.343
 174.515 174.677 174.547   175.4   176.1   176.5   176.2   176.9   175.7   175.6
   176.6
                                                                                
                                                                                
        
  4064.4  4477.7  4687.7  4817.7  4857.7  4904.7  4934.3  4998.2    5000    5059
    5107    5155    5210  5353.8  5563.8  5923.8  6043.8  6073.8  6133.8  6363.8
  7005.7
  174.99   174.7   174.3   174.1   174.1  173.56  173.83  174.19 174.243 174.343
 174.515 174.677 174.547   175.4   176.1   176.5   176.2   176.9   175.7   175.6
   176.6
                                                                                
                                                                                
        
BR Coef= 1 , 1 , 0 ,1.25, 0 ,,,0.8,-1,2,0,
WSPro=,,,, 1 ,,,, 0 ,,,, 0 ,,,,-1 ,-1 ,-1 , 0 , 0 , 0 , 0 , 0
Culvert=1,3,,26,0.015,0.4,1,1,3,170.07,4999.1,169.98,4999.1,Culvert #1  , 0 ,10
Culvert Bottom n=0.015
BC Design=,, 0 ,, 0 ,,,,,,
BC HTab HWMax=176.93

Type RM Length L Ch R = 1 ,6880.6  ,105,102.6,102
BEGIN DESCRIPTION:
PRIVATE DRIVE - XS 2
Interpolated channel - LIDAR overbanks
Downstream Section of Bridge/Culvert/Weir
END DESCRIPTION:
XS GIS Cut Line= 5
     2967393.926    13911130.843      2966340.49    13909615.318
     2965750.167    13909249.895     2965476.849    13909078.569
     2964055.653    13908196.264
#Sta/Elev= 30
  2324.4  178.01  2504.4  177.34  2524.4  176.68  2814.4  177.17  2894.4  176.36
  3564.4  174.77  3584.4   175.2  4064.4  174.99  4084.4  174.45  4154.4  174.99
  4539.5  173.39  4849.5     174  4894.3  173.04  4992.3  173.05  5000.1   170.5
  5004.9  172.08  5022.3  173.82  5314.9  175.58  5764.9  176.29  5794.9  175.68
  5804.9  176.23  6004.9  177.05  6044.9  175.96  6064.9     177  6134.9  176.24
  6234.9  176.75  6374.9  175.77  6384.9  176.19  6394.9   175.6  6839.3  176.13
#Mann= 4 ,-1 , 0
  2324.4     .99       0  4064.4     .06       0  4992.3     .04       0
  5022.3     .06       0
#XS Ineff= 2 , 0
       0    4986     173    5010       0   173.5
Permanent Ineff=
       F       F
Bank Sta=4992.3,5022.3
Exp/Cntr=0.5,0.3

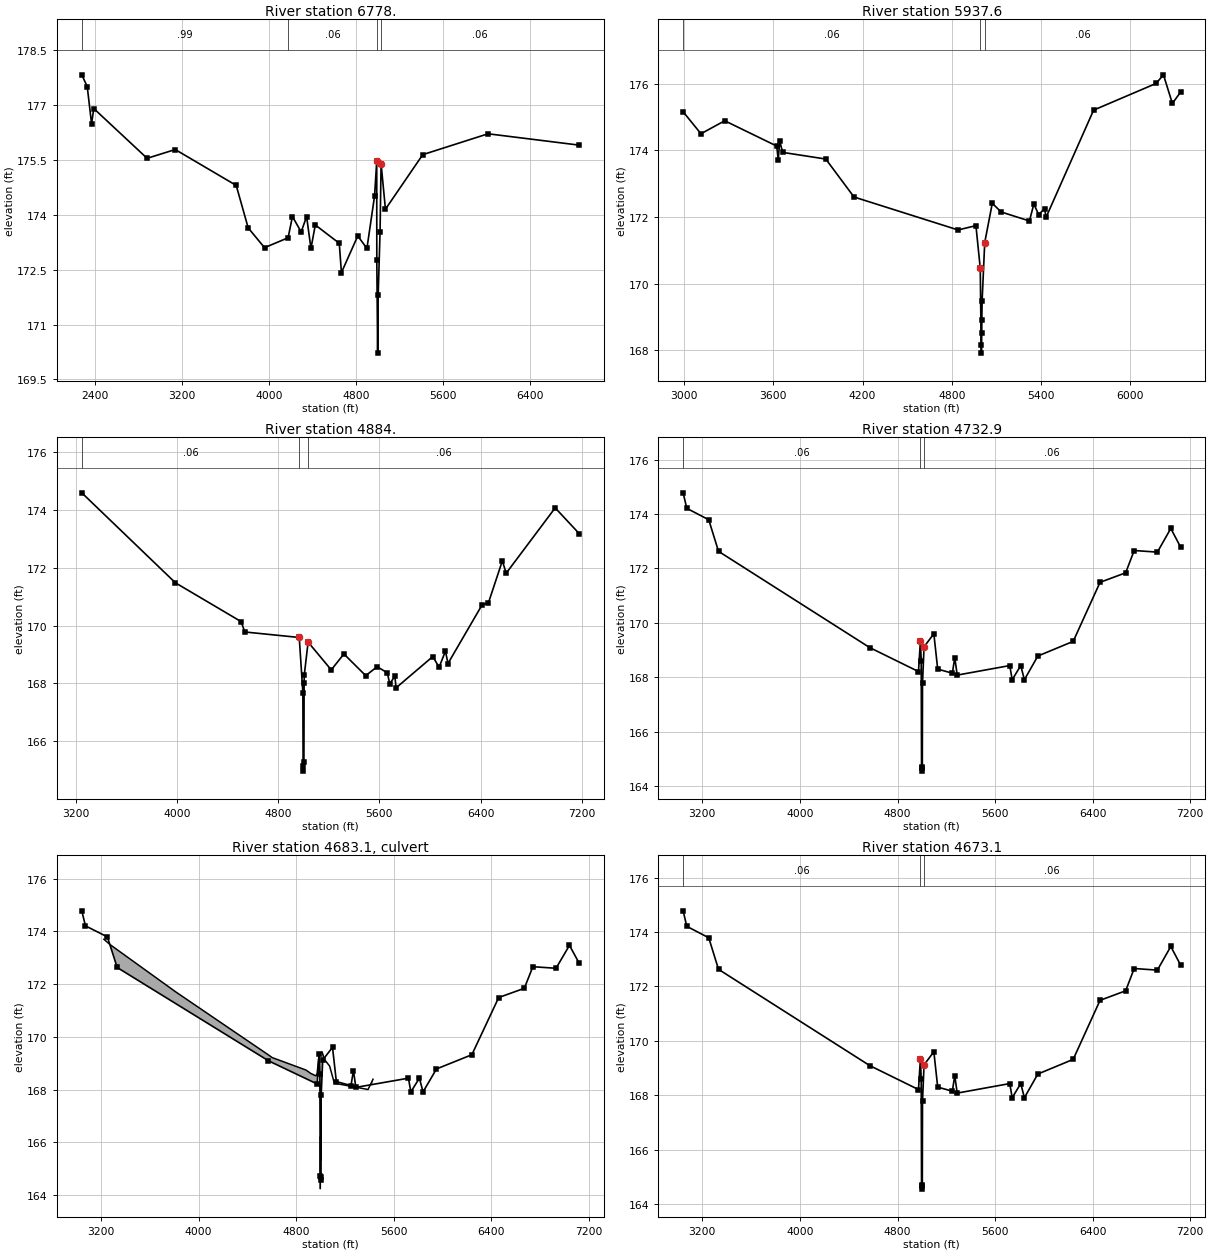
Type RM Length L Ch R = 1 ,6778.   ,403,840.4,848
BEGIN DESCRIPTION:
PRIVATE DRIVE - XS 1
Interpolated channel - LIDAR overbanks
END DESCRIPTION:
XS GIS Cut Line= 6
      2967469.04     13911078.57      2966387.53     13909522.66
      2965797.21     13909157.24      2965523.89     13908985.91
      2964827.32     13908553.47      2964116.02     13908111.88
#Sta/Elev= 30
  2282.6  177.82  2332.6   177.5  2372.6  176.48  2392.6   176.9  2882.6  175.54
    3141  175.78    3701   174.8    3811  173.64    3961   173.1  4177.5  173.37
  4217.5  173.95  4297.5  173.53  4347.5  173.95  4387.5  173.08  4427.5  173.72
  4647.5  173.22  4667.5  172.42  4817.5  173.42  4901.7  173.08  4971.7  174.51
  4991.7  175.46  4992.3  172.77  5000.1  170.22  5004.9   171.8  5022.3  173.54
  5031.7  175.39  5071.7  174.15  5414.3  175.64  6014.2  176.21  6851.4   175.9
#Mann= 4 ,-1 , 0
  2282.6     .99       0  4177.5     .06       0  4991.7     .04       0
  5031.7     .06       0
Bank Sta=4991.7,5031.7
Exp/Cntr=0.3,0.1

Type RM Length L Ch R = 1 ,5937.6  ,901,1053.6,1078
BEGIN DESCRIPTION:
Interpolated XS
END DESCRIPTION:
XS GIS Cut Line= 4
      2967452.36    13910552.349      2966587.65    13909607.866
      2966310.85    13908530.813     2965429.204     13908163.61
#Sta/Elev= 30
  2992.6  175.16  3112.6   174.5  3272.6  174.89  3622.6  174.13  3632.6  173.71
  3642.6  174.28  3662.6  173.94  3952.6  173.74  4142.6   172.6  4843.1  171.61
  4963.1  171.74  4992.3  170.46  4998.3  168.16  5000.1  167.91  5002.3  168.51
  5002.9  168.92  5004.9  169.49  5022.3  171.23  5073.1  172.41  5133.1  172.15
  5323.1  171.88  5353.1  172.39  5385.2  172.07  5425.2  172.25  5435.2  171.99
  5755.2  175.21  6175.2  176.01  6225.2  176.27  6285.2  175.41  6340.2  175.75
#Mann= 3 ,-1 , 0
  2992.6     .06       0  4992.3     .04       0  5022.3     .06       0
Bank Sta=4992.3,5022.3
Exp/Cntr=0.3,0.1

Type RM Length L Ch R = 1 ,4884.   ,167,151.1,38
BEGIN DESCRIPTION:
WARREN RANCH ROAD - XS 4
Interpolated channel - LIDAR overbanks
END DESCRIPTION:
XS GIS Cut Line= 6
      2967332.49     13910376.97      2967303.36     13909488.56
      2967268.41     13908699.18      2967373.63     13908549.53
      2967355.43     13908167.22       2965862.6     13907380.76
#Sta/Elev= 30
  3247.5  174.59  3987.5  171.48  4506.4  170.14  4536.4  169.78  4966.5  169.59
 4995.21  167.68 4997.09  165.14 4999.49  164.97 5003.39  165.28 5005.04  168.01
  5006.5   168.3  5036.5  169.43  5219.5  168.47  5319.5  169.02  5492.2  168.27
  5582.2  168.58  5662.2  168.37  5682.2  167.99  5722.2  168.25  5732.2  167.85
  6022.2  168.93  6072.2  168.56  6122.2  169.12  6142.2  168.69  6412.2  170.72
  6462.2  170.79  6572.2  172.24  6602.2  171.81  6989.7  174.07  7179.6  173.18
#Mann= 3 ,-1 , 0
  3247.5     .06       0  4966.5     .05       0  5036.5     .06       0
Bank Sta=4966.5,5036.5
Exp/Cntr=0.5,0.3

Type RM Length L Ch R = 1 ,4732.9  ,59.8,59.8,59.8
BEGIN DESCRIPTION:
WARREN RANCH ROAD - XS 3
Interpolated channel - LIDAR overbanks
Upstream Section of Bridge/Culvert/Weir
END DESCRIPTION:
XS GIS Cut Line= 4
      2967471.89     13910528.98      2967408.57     13908643.46
      2967384.14     13908143.35      2965895.79     13907343.01
#Sta/Elev= 30
  3042.7  174.78  3072.7  174.21  3252.7  173.79  3332.7  172.63  4572.7  169.09
  4971.9  168.21  4987.8  169.35  4994.2   168.6  4996.9  164.71  4999.4  164.55
  5003.2  164.68  5004.8  167.78  5017.6  169.12  5097.8   169.6  5129.3   168.3
  5249.3  168.15  5269.3  168.72  5289.3  168.08    5720  168.43    5740  167.91
    5810  168.43    5840  167.91    5950  168.78    6240  169.32    6460  171.49
    6670  171.84    6740  172.66    6930   172.6    7040  173.47  7119.9  172.79
#Mann= 3 ,-1 , 0
  3042.7     .06       0  4987.8     .07       0  5017.6     .06       0
#XS Ineff= 2 , 0
       0    4987  168.21    5013       0  167.91
Permanent Ineff=
       F       F
Bank Sta=4987.8,5017.6
Exp/Cntr=0.5,0.3

Type RM Length L Ch R = 2 ,4683.1  ,,,
BEGIN DESCRIPTION:
WARREN RANCH ROAD
Structure ID: K160-01-00-S1
END DESCRIPTION:
Bridge Culvert--1,0,-1,-1, 0
Deck Dist Width WeirC Skew NumUp NumDn MinLoCord MaxHiCord MaxSubmerge Is_Ogee
10,28,3,0, 18, 18, , , 0.95, 0, ,,,
  3224.1  3274.1  3814.1  4576.7  4604.1  4873.6  4883.1  4919.7  4956.4  4963.3
  4971.9  4987.8    5012    5033    5074    5113    5389    5430
   173.7   173.5   171.7   169.3  169.21  168.75  168.73  168.61  168.53  168.52
  168.62  169.33  169.43  169.13  168.89  168.24     168  168.39
                                                                                
                                                                
  3224.1  3274.1  3814.1  4576.7  4604.1  4873.6  4883.1  4919.7  4956.4  4963.3
  4971.9  4987.8    5012    5033    5074    5113    5389    5430
   173.7   173.5   171.7   169.3  169.21  168.75  168.73  168.61  168.53  168.52
  168.62  169.33  169.43  169.13  168.89  168.24     168  168.39
                                                                                
                                                                
BR Coef= 1 , 1 , 0 ,1.25, 0 ,,,0.8,-1,2,0,
WSPro=,,,, 1 ,,,, 0 ,,,, 0 ,,,,-1 ,-1 ,-1 , 0 , 0 , 0 , 0 , 0
Culvert=1,2,,28,0.015,0.4,1,1,3,164.22,4998.1,164.33,4998.1,Culvert #1  , 0 ,10
Culvert Bottom n=0.015
Culvert=1,2,,28,0.015,0.4,1,1,3,165.3,5002.6,164.3,5002.6,Culvert #2  , 0 ,10
Culvert Bottom n=0.015
BC Design=,, 0 ,, 0 ,,,,,,
BC HTab HWMax=174.78

Type RM Length L Ch R = 1 ,4673.1  ,125.1,125.1,57
BEGIN DESCRIPTION:
WARREN RANCH ROAD - XS 2
Interpolated channel - LIDAR overbanks
Downstream Section of Bridge/Culvert/Weir
END DESCRIPTION:
XS GIS Cut Line= 4
      2967512.96     13910521.74      2967456.98     13908827.77
      2967437.69     13908096.24      2965921.83      13907277.9
#Sta/Elev= 30
  3042.7  174.78  3072.7  174.21  3252.7  173.79  3332.7  172.63  4572.7  169.09
  4971.9  168.21  4987.8  169.35  4994.2   168.6  4996.9  164.71  4999.4  164.55
  5003.2  164.68  5004.8  167.78  5017.6  169.12  5097.8   169.6  5129.3   168.3
  5249.3  168.15  5269.3  168.72  5289.3  168.08    5720  168.43    5740  167.91
    5810  168.43    5840  167.91    5950  168.78    6240  169.32    6460  171.49
    6670  171.84    6740  172.66    6930   172.6    7040  173.47  7119.9  172.79
#Mann= 3 ,-1 , 0
  3042.7     .06       0  4987.8     .07       0  5017.6     .06       0
#XS Ineff= 2 , 0
       0    4987     167    5013       0     167
Permanent Ineff=
       F       F
Bank Sta=4987.8,5017.6
Exp/Cntr=0.5,0.3

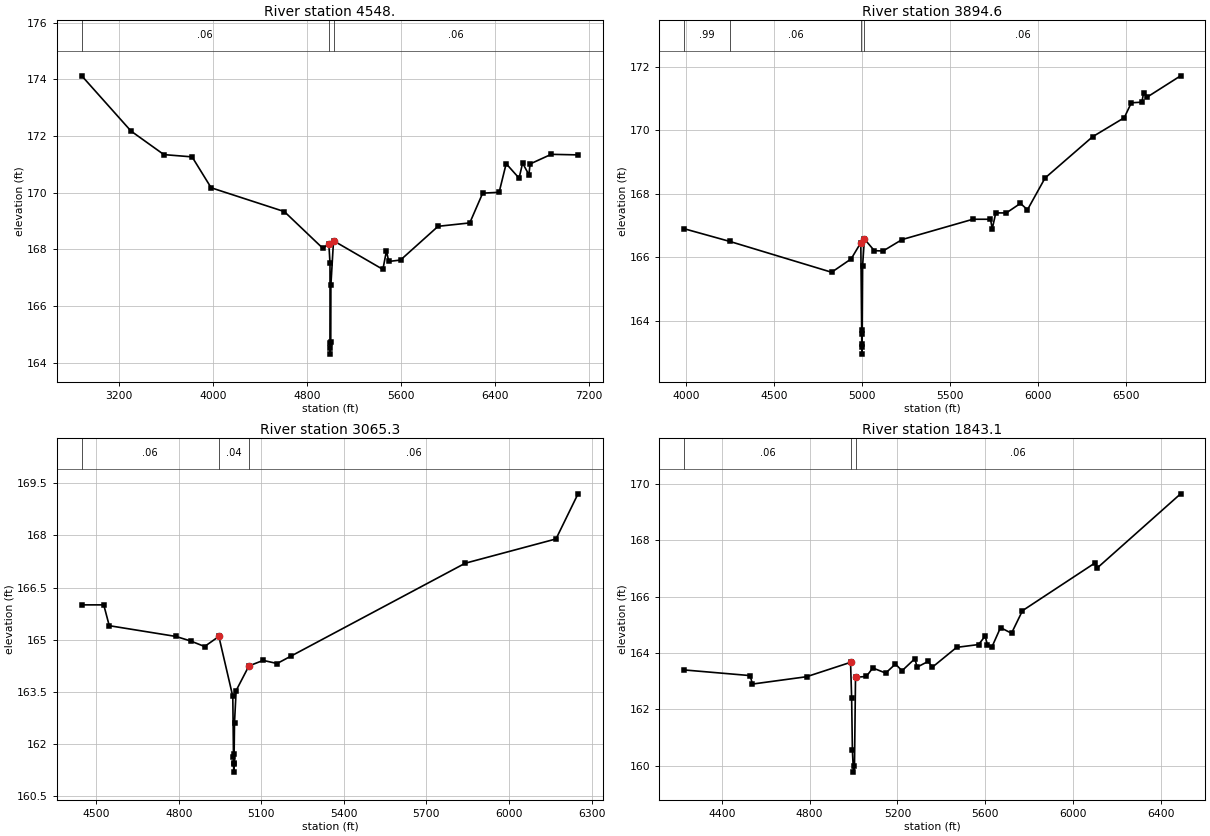
Type RM Length L Ch R = 1 ,4548.   ,706,653.4,421
BEGIN DESCRIPTION:
WARREN RANCH ROAD - XS 1
Interpolated channel - LIDAR overbanks
END DESCRIPTION:
XS GIS Cut Line= 6
       2967606.3     13910516.78      2967542.21     13908792.39
      2967545.13     13908463.24      2967453.09     13908391.73
      2967445.13      13908037.7      2965947.38     13907229.14
#Sta/Elev= 30
  2881.9  174.12  3301.9  172.17  3581.9  171.34  3821.9  171.26  3984.2  170.17
  4607.5  169.33  4936.7  168.03  4986.7   168.2  4996.7  167.51 4997.03   164.7
 4997.16  164.52 4999.49   164.3 5003.14  164.72 5004.25  166.73  5026.7   168.3
  5447.3  167.29  5477.3  167.94  5497.3  167.57  5597.3  167.62  5917.3  168.81
  6187.3  168.93  6297.3  169.98  6437.3  170.01  6497.3  171.02  6607.3  170.51
  6637.3  171.04    6691  170.63    6701  171.01    6881  171.35  7109.4  171.33
#Mann= 3 ,-1 , 0
  2881.9     .06       0  4986.7     .05       0  5026.7     .06       0
Bank Sta=4986.7,5026.7
Exp/Cntr=0.3,0.1

Type RM Length L Ch R = 1 ,3894.6  ,984,829.3,683
BEGIN DESCRIPTION:
Cross Section K160-01-00-X3
Overflow to/from K160-00-00 on far LOB
END DESCRIPTION:
XS GIS Cut Line= 4
       2968430.8     13908863.08      2968044.42      13908171.1
      2967791.54     13907827.11 2966557.296662313906808.9862085
#Sta/Elev= 30
  3990.7   166.9    4250   166.5  4827.6  165.53  4938.4  165.95  4993.4  166.46
  4998.5   163.6  4998.8  163.26    5000  162.95  5000.9  163.19  5001.6  163.72
  5003.7  165.73  5013.6  166.58  5070.4  166.21  5119.8   166.2  5227.8  166.56
  5630.2   167.2  5730.2   167.2  5740.2   166.9  5760.2   167.4  5820.2   167.4
  5900.2   167.7  5940.2   167.5  6040.2   168.5  6310.2   169.8  6490.2   170.4
  6530.2  170.87  6590.2  170.89  6600.2  171.19  6620.2  171.05  6810.2  171.72
#Mann= 4 ,-1 , 0
  3990.7     .99       0    4250     .06       0  4993.4     .04       0
  5013.6     .06       0
Bank Sta=4993.4,5013.6
Exp/Cntr=0.3,0.1

Type RM Length L Ch R = 1 ,3065.3  ,1125.2,1222.2,1269.4
BEGIN DESCRIPTION:
Cross Section K160-01-00-X2
END DESCRIPTION:
XS GIS Cut Line= 4
      2968849.79     13907749.94      2968592.93     13907475.23
      2968263.23     13907312.97 2967299.834439413906870.8136295
#Sta/Elev= 22
  4447.3     166  4527.3     166  4547.3   165.4  4789.6  165.09  4842.8  164.96
  4893.8   164.8  4945.6  165.09  4996.3  163.36  4998.8  161.63  4998.9  161.45
  4999.9  161.18    5001  161.42  5001.1   161.7  5002.5   162.6  5008.4  163.53
  5054.8  164.24  5106.7   164.4  5157.3  164.31  5209.3  164.53  5840.9   167.2
  6170.9   167.9  6250.9   169.2
#Mann= 3 ,-1 , 0
  4447.3     .06       0  4945.6     .04       0  5054.8     .06       0
Bank Sta=4945.6,5054.8
Exp/Cntr=0.3,0.1

Type RM Length L Ch R = 1 ,1843.1  ,0,0,0
BEGIN DESCRIPTION:
Cross Section K160-01-00-X1
END DESCRIPTION:
XS GIS Cut Line= 4
      2969468.89      13907230.9      2969232.01     13906671.88
      2969048.35      13906406.5 2968034.816259913905545.2411132
#Sta/Elev= 30
  4229.3   163.4  4529.3   163.2  4539.3   162.9  4785.9  163.16  4986.3  163.67
  4991.2  162.42  4994.7  160.55  4999.5  159.78  5004.2  159.99  5008.9  163.14
  5058.2  163.17  5087.5  163.47  5146.2  163.29  5190.8  163.61  5220.6  163.37
  5279.2   163.8  5289.2   163.5  5339.2   163.7  5359.2   163.5  5469.2   164.2
  5569.2   164.3  5599.2   164.6  5609.2   164.3  5629.2   164.2  5669.2   164.9
  5719.2   164.7  5769.2   165.5  6099.2  167.19  6109.2  167.01  6489.2  169.64
#Mann= 3 ,-1 , 0
  4229.3     .06       0  4986.3     .04       0  5008.9     .06       0
Bank Sta=4986.3,5008.9
Exp/Cntr=0.3,0.1

Chan Stop Cuts=-1
Use User Specified Reach Order=0
User Specified Reach Order=K160-01-00      ,K160-01-00_0018